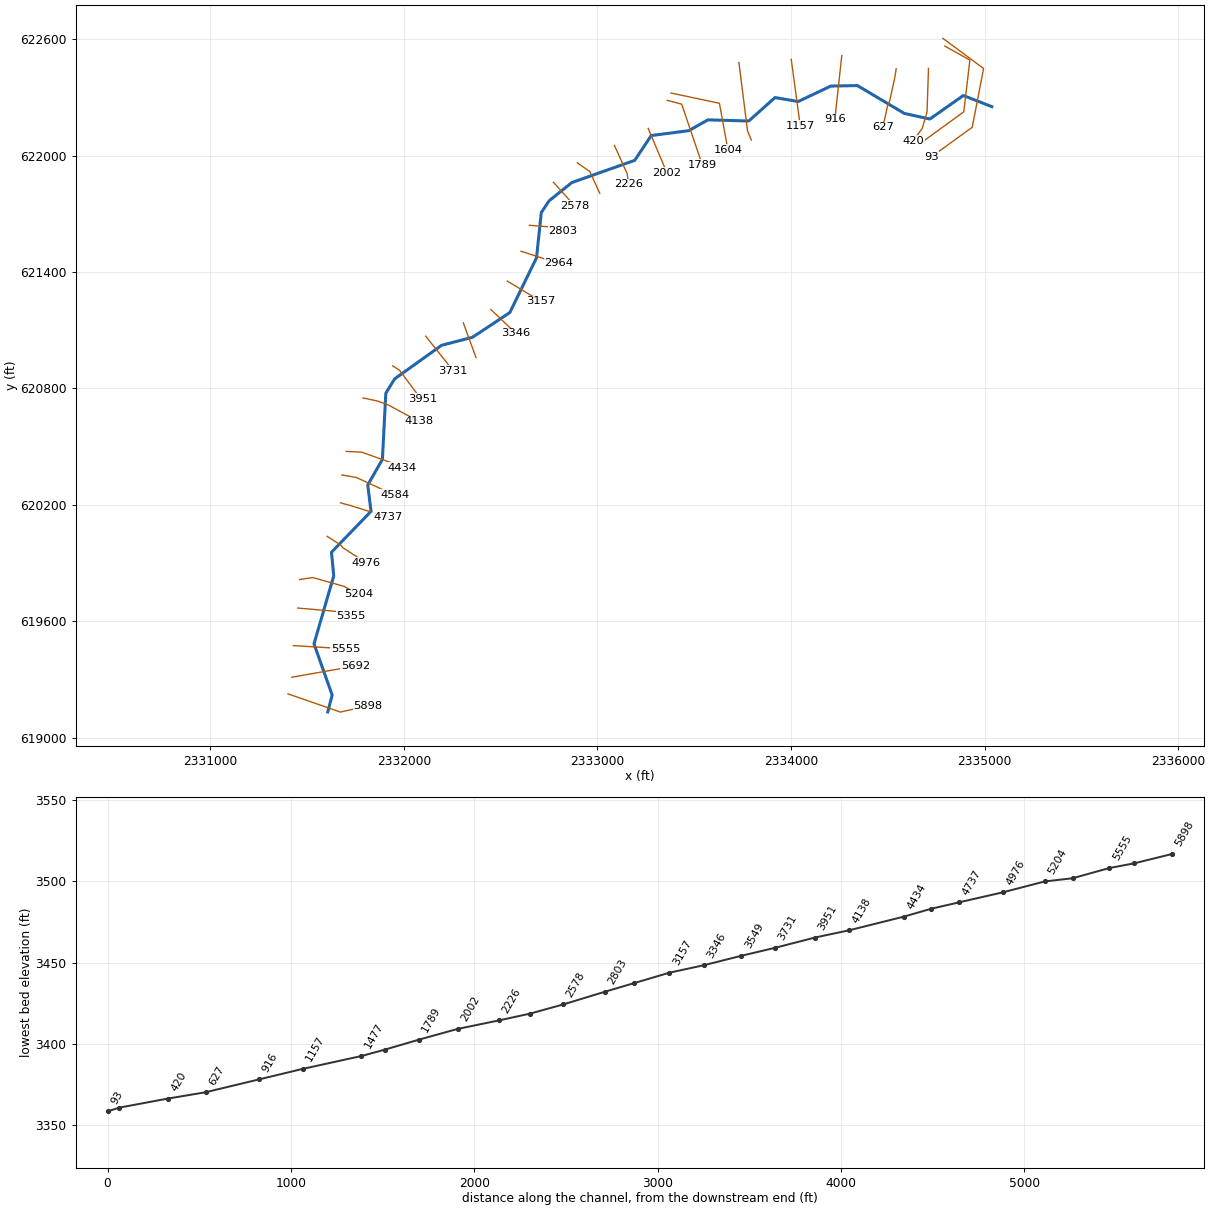
--- CAMPFIVERN.prj (project) ---

Proj Title=CAMPFIVERN
Current Plan=p01
Default Exp/Contr=0,0
English Units
Geom File=g01
Flow File=f01
Plan File=p01
Background Map Layer=Inundation Boundary (P100yr Value_0)
BEGIN DESCRIPTION:
----------MODEL BY WOOD PLC 2022----------
AFH study
Randolph County, WV
HEC-RAS Version: RAS 6.2
Vertical Datum: NAVD88
Projection: NAD 1983 StatePlane West Virginia S FIPS 4702 (US Feet)
Terrain: 1-meter LIDAR (FEMA Region III 3DEP collected 2016-2018)
Land Use: 2019 NLCD
Hydrologic Method:
WV SIR2010-5033 regression equations
Additional Model Notes:
None
END DESCRIPTION:
DSS Export Rating Curves= 0
DSS Export Rating Curve Sorted= 0
DSS Export Volume Flow Curves= 0
DXF OffsetX= 0
DXF OffsetY= 0
DXF ScaleX= 0
DXF ScaleY= 0

--- CAMPFIVERN.p01 (plan) ---

Plan Title=Floodplain
Program Version=6.20
Short Identifier=Floodplain
Geom File=g01
Flow File=f01
Subcritical Flow
K Sum by GR= 0
Std Step Tol= 0.01
Critical Tol= 0.01
Num of Std Step Trials= 20
Max Error Tol= 0.3
Flow Tol Ratio= 0.001
Split Flow NTrial= 30
Split Flow Tol= 0.02
Split Flow Ratio= 0.02
Log Output Level= 0
Friction Slope Method= 1
Unsteady Friction Slope Method= 2
Unsteady Bridges Friction Slope Method= 1
Parabolic Critical Depth
Global Vel Dist= 0 , 0 , 0
Global Log Level= 0
CheckData=True
Encroach Param=-1 ,0,0, 0
Mapping Interval=1HOUR
Computation Time Step Use Courant=        0
Computation Time Step Use Time Series=    0
Computation Time Step Count To Double=0
Computation Time Step Max Doubling=0
Computation Time Step Max Halving=0
Computation Time Step Residence Courant=0
Run HTab= 0
Run UNet= 0
Run Sediment= 0
Run PostProcess= 0
Run WQNet= 0
Run RASMapper=-1
UNET Theta= 0
UNET Theta Warmup= 0
UNET ZTol= 0
UNET ZSATol= 0
UNET MxIter= 0
UNET Max Iter WO Improvement= 0
UNET MaxInSteps= 0
UNET DtIC= 0
UNET DtMin= 0
UNET MaxCRTS= 0
UNET WFStab= 0
UNET SFStab= 0
UNET WFX= 1
UNET SFX= 1
UNET Gravity=32.174
UNET 1D Methodology=Finite Difference
UNET DSS MLevel= 1
UNET Pardiso=0
UNET DZMax Abort= 0
UNET Use Existing IB Tables= 0
UNET Froude Reduction=False
UNET Froude Limit= 0
UNET Froude Power= 0
UNET D1 Cores= 0
UNET WindReference=Eulerian
UNET WindDragFormulation=Hsu (1988)
UNET D2 Coriolis=0
UNET D2 Cores= 0
UNET D2 Theta= 1
UNET D2 Theta Warmup= 1
UNET D2 Z Tol= 0.01
UNET D2 Volume Tol= 0.01
UNET D2 Max Iterations= 20
UNET D2 Equation= 0
UNET D2 RampUpFraction=0.1
UNET D2 TimeSlices= 1
UNET D2 Turbulence Formulation=Non-Conservative (original)
UNET D2 Eddy Viscosity=0.3
UNET D2 Transverse Eddy Viscosity=0.1
UNET D2 Smagorinsky Mixing=0
UNET D2 BCVolumeCheck=0
UNET D2 Cores=0
UNET D2 SolverType=PARDISO (Direct)
UNET D2 Minimum Iterations= 2147483647
UNET D2 Maximum Iterations= 2147483647
UNET D2 Restart Number= 10
UNET D2 Relaxation Coeff=1.3
UNET D2 SOR Precondition Iterations= 10
UNET D2 ILUT Maximum Fill= 8
UNET D2 ILUT Tolerance=1E-08
UNET D1D2 MaxIter= 0
UNET D1D2 ZTol=0.01
UNET D1D2 QTol=0.1
UNET D1D2 MinQTol=1
Write IC File= 0
Write IC File at Fixed DateTime=0
Write IC File at Sim End=0
Echo Input=False
Echo Parameters=False
Echo Output=False
Write Detailed= 0
HDF Write Warmup=0
HDF Write Time Slices=0
HDF Flush=0
HDF Compression= 1
HDF Chunk Size= 1
HDF Spatial Parts= 1
HDF Use Max Rows=0
HDF Fixed Rows= 1
Calibration Method= 0
Calibration Iterations= 20
Calibration Max Change=0.05
Calibration Tolerance=0.2
Calibration Maximum=1.5
Calibration Minimum=0.5
Calibration Optimization Method= 1
WQ AD Non Conservative
WQ ULTIMATE=-1
WQ Max Comp Step=1HOUR
WQ Output Interval=15MIN
WQ Output Selected Increments= 0
WQ Output face flow=0
WQ Output face velocity=0
WQ Output face area=0
WQ Output face dispersion=0
WQ Output cell volume=0
WQ Output cell surface area=0
WQ Output cell continuity=0
WQ Output cumulative cell continuity=0
WQ Output face conc=0
WQ Output face dconc_dx=0
WQ Output face courant=0
WQ Output face peclet=0
WQ Output face adv mass=0
WQ Output face disp mass=0
WQ Output cell mass=0
WQ Output cell source sink temp=0
WQ Output nsm pathways=0
WQ Output nsm derived pathways=0
WQ Create Restart=0
WQ Fixed Restart=0
WQ System Summary=0
WQ Write To DSS=0
Sorting and Armoring Iterations= 10
XS Update Threshold= 0.02
Bed Roughness Predictor= 0
Hydraulics Update Threshold= 0.02
Energy Slope Method= 1
Volume Change Method= 1
Sediment Retention Method= 0
Sediment TS Multiplier= 1
Warm Up Method= 0
XS Weighting Method= 0
Number of US Weighted Cross Sections= 1
Number of DS Weighted Cross Sections= 1
Upstream XS Weight=0
Main XS Weight=1
Downstream XS Weight=0
Number of DS XS's Weighted with US Boundary= 1
Upstream Boundary Weight= 1
Weight of XSs Associated with US Boundary= 0
Number of US XS's Weighted with DS Boundary= 1
Downstream Boundary Weight= 0.5
Weight of XSs Associated with DS Boundary= 0.5
Percentile Method= 0
Sediment Output Level= 3
Mass or Volume Output= 0
Output Increment Type= 1
Profile and TS Output Increment= 1
Transport Output Increment 1
XS Output Flag= 0
XS Output Increment= 10
Read HDF5 Sediment Hotstart= 0
Sediment Hotstart Type= 0
Write Gradation File= 0
Read Gradation Hotstart= 0
Write HDF5 File= 1
Write Binary Output= 1
Write DSS Sediment File= 0
DSS Sediment Output Type= 1
SV Curve= 0
Specific Gage Flag= 0
Subcell Erosion Methods= 0
Subcell Deposition Methods= 0
Advection Scheme= 1
Matrix Solver= 0
Implicit Weighting Factor= 1
Maximum Outer Loop Convergence Iterations= 5
Convergence Maximum Absolute= 0.001
Convergence RMSE= 0.0001
Grain Fractions Max Abs Error= 0.001
Max Subgrid Regions= 1
Max Subgrid Length Scale= 3.402823E+38
Initial Layer Thickness= 3.402823E+38
Min Layer Thickness= 3.402823E+38
Max Layer Thickness= 3.402823E+38
Number of Layers= 5

--- CAMPFIVERN.f01 (steady flow) ---

Flow Title=Flow
Program Version=6.20
Number of Profiles= 1
Profile Names=P100yr
River Rch & RM=CAMPFIVERN,Main            ,5898
     335
River Rch & RM=CAMPFIVERN,Main            ,4976
     384
River Rch & RM=CAMPFIVERN,Main            ,4434
     428
River Rch & RM=CAMPFIVERN,Main            ,1477
     544
Boundary for River Rch & Prof#=CAMPFIVERN,Main            , 1
Up Type= 0
Dn Type= 3
Dn Slope=0.027163
DSS Import GetInterval= 0
DSS Import GetPeak= 0
DSS Import FillOption= 0

--- CAMPFIVERN.g01 (geometry) ---

Geom Title=Geometry
Program Version=6.20

River Reach=CAMPFIVERN      ,Main
Reach XY= 30
2331606.62893417619132.4179940372331629.63814899619219.416421413
2331535.77146293619483.2561454922331637.79800001619834.191000015
2331626.07900003619955.7189999972331830.19293624 620166.60822551
2331813.48500003      620302.3382331889.10000002620434.452000022
2331906.66300002620775.4529999942331952.49600001620849.758000016
2332194.85800001621022.6749999972332354.58000001621063.994000018
2332547.28799999621191.4249999972332685.13500004621474.063999996
2332709.78799999621707.0500000122332750.06600003621767.467000008
2332867.42700005621861.5640000252333192.42700003      621976.147
2333277.49599999622103.9250000122333471.94100001      622129.272
2333570.17800003622184.844000012     2333781.273622178.939999998
2333917.01442839622299.8197918982334036.61500004622279.386000007
2334205.03000003      622359.081     2334342.495622361.651999995
2334584.96000001      622217.9632334716.62700002622189.153999999
2334889.71600002 622310.348000022335036.68441947 622252.92200093

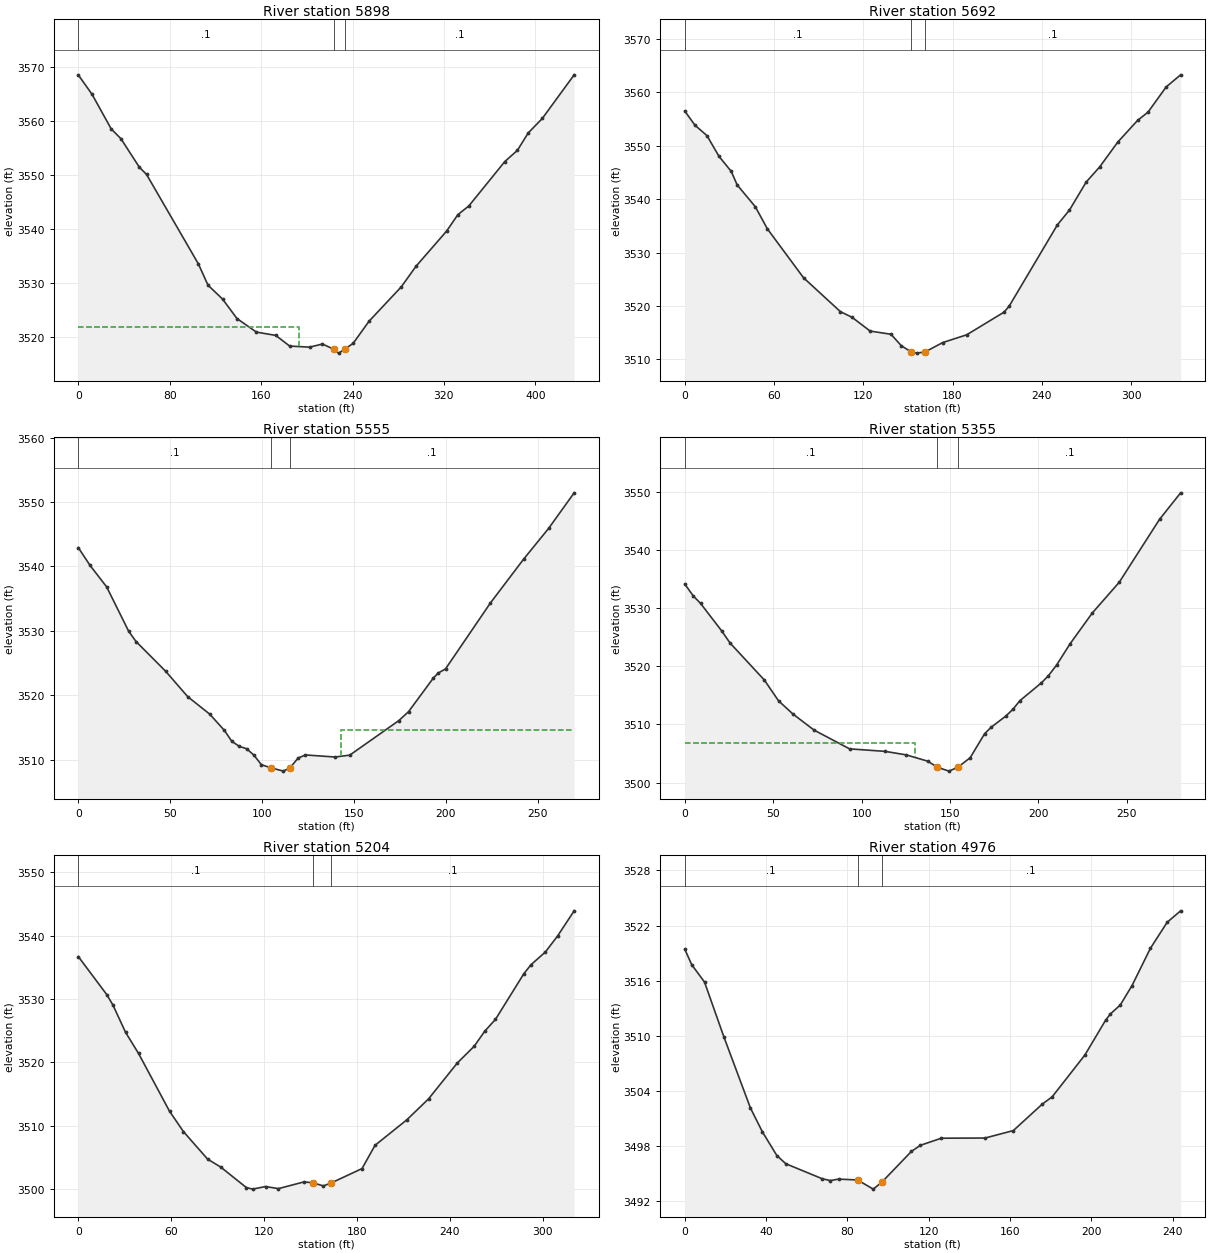
Type RM Length L Ch R = 1 ,5898    ,202,205.8,207.1
XS GIS Cut Line= 3
2331400.93110558619225.8523021142331672.17729762619131.678807567
2331815.42712031619164.175295122
#Sta/Elev= 30
       0 3568.54    11.9 3564.99    28.8 3558.53    37.3 3556.71    53.4 3551.43
    59.7 3550.09   105.1 3533.48   113.5 3529.54   126.2 3526.97   138.9 3523.34
   155.9 3520.83   172.8 3520.22     185 3518.24   202.4 3518.04   213.7 3518.62
   223.6 3517.65   227.8 3516.93   233.1 3517.64   240.6 3518.76   254.5 3522.86
   282.6 3529.21   295.7 3533.08   322.3 3539.56   332.2 3542.62   341.9 3544.26
   373.3 3552.48   384.3 3554.55   393.8 3557.79   406.1 3560.47     434 3568.57
#Mann= 3 ,-1,0
       0      .1       0   223.6    .045       0   233.1      .1       0
#XS Ineff= 2 , 0
          192.78  3521.8
Permanent Ineff=
       F       F
Bank Sta=223.6,233.1
XS Rating Curve= 0 ,0
Exp/Cntr(USF)=0,0
Exp/Cntr=0.3,0.1

Type RM Length L Ch R = 1 ,5692    ,136.7,137,134
XS GIS Cut Line= 2
2331421.49010791619311.4042795542331749.77095158619369.102124805
#Sta/Elev= 30
       0 3556.49     6.8 3553.85    14.9 3551.89      23 3548.01    31.2 3545.21
    35.2 3542.67    47.4 3538.59    55.5 3534.45    79.8  3525.3   104.6 3518.95
   112.4  3517.9   124.6 3515.32   138.6 3514.72   145.5 3512.59     1523511.441
   155.8 3511.19   161.63511.424   173.3 3513.16   189.5 3514.62   214.6 3518.86
     218 3519.96   250.5 3535.21   258.6 3537.97   269.8  3543.2   278.9 3546.04
   291.1  3550.7   304.4 3554.75   311.4 3556.29   323.6 3561.01   333.3 3563.27
#Mann= 3 ,-1,0
       0      .1       0     152    .045       0   161.6      .1       0
Bank Sta=152,161.6
XS Rating Curve= 0 ,0
Exp/Cntr(USF)=0,0
Exp/Cntr=0.3,0.1

Type RM Length L Ch R = 1 ,5555    ,199.1,200.4,198.9
XS GIS Cut Line= 2
2331428.78523777619474.5499109522331698.04184894619457.970070363
#Sta/Elev= 30
       0 3542.92     6.4 3540.16    15.4 3536.84    27.4 3529.95    31.4 3528.36
    47.5 3523.75    59.5 3519.81    71.5 3517.09    79.5 3514.56    83.5 3512.88
    87.6 3512.09    91.6 3511.72    95.6 3510.71    99.6 3509.25   104.6 3508.78
   111.6 3508.25   115.33508.805   119.6 3510.28   123.6 3510.76   139.7 3510.44
   147.7 3510.73   174.4 3516.09   179.7 3517.48   193.2  3522.7   195.8 3523.46
   199.8 3524.11   224.2 3534.33   242.3 3541.14   255.9 3545.91   269.8 3551.43
#Mann= 3 ,-1,0
       0      .1       0   104.6    .045       0   115.3      .1       0
#XS Ineff= 1 ,-1
  142.69269.7666 3514.68
Permanent Ineff=
       F
Bank Sta=104.6,115.3
XS Rating Curve= 0 ,0
Exp/Cntr(USF)=0,0
Exp/Cntr=0.3,0.1

Type RM Length L Ch R = 1 ,5355    ,150.9,151.2,149.2
XS GIS Cut Line= 3
2331451.34708485619668.1294977362331666.22181888619649.327958508
2331727.46111808 619628.37767194
#Sta/Elev= 30
       0 3534.14     4.8  3532.1     8.9 3530.82    20.9 3526.07    25.6    3524
      45 3517.63      53 3514.06    61.1  3511.8    73.1 3509.02    93.2 3505.79
   113.3 3505.36   125.3 3504.75   137.4 3503.67   142.9 3502.62   149.4 3501.96
   154.5 3502.64   161.4 3504.27   169.6 3508.42   173.3 3509.52   181.5 3511.42
   185.5 3512.58   189.5 3514.08   201.6 3517.13   205.6 3518.36   210.3 3520.23
   217.8 3523.83   230.4 3529.15   245.7 3534.46   268.5 3545.29   280.4 3549.84
#Mann= 3 ,-1,0
       0      .1       0   142.9    .045       0   154.5      .1       0
#XS Ineff= 2 , 0
          129.96 3506.73
Permanent Ineff=
       F       F
Bank Sta=142.9,154.5
XS Rating Curve= 0 ,0
Exp/Cntr(USF)=0,0
Exp/Cntr=0.3,0.1

Type RM Length L Ch R = 1 ,5204    ,230.3,227.7,223.9
XS GIS Cut Line= 4
2331461.98365678619815.0828761912331529.13201117619825.289426058
 2331691.8996222619779.6285450752331764.41984494619738.802345608
#Sta/Elev= 30
       0 3536.69    18.4 3530.68    22.4 3529.02    30.5 3524.74    38.9  3521.4
    58.9 3512.29    67.9 3509.07    83.5 3504.73    91.9 3503.49   108.5 3500.25
   112.6    3500   120.9 3500.41   129.2 3500.08   145.9 3501.15   151.6 3500.98
   158.3 3500.51   163.43500.987   183.2 3503.24   191.6 3506.91   212.3 3510.97
   226.2 3514.25   244.8 3519.92   255.6 3522.53   262.5 3524.93   269.4 3526.79
   287.8 3534.02   292.4 3535.42   301.6 3537.41   309.5 3539.94   320.2 3543.91
#Mann= 3 ,-1,0
       0      .1       0   151.6    .045       0   163.4      .1       0
Bank Sta=151.6,163.4
XS Rating Curve= 0 ,0
Exp/Cntr(USF)=0,0
Exp/Cntr=0.3,0.1

Type RM Length L Ch R = 1 ,4976    ,234.5,239.2,242.1
XS GIS Cut Line= 4
2331604.02586072620037.682796458  2331673.316024619993.097561058
2331685.26659653619978.9062561882331805.20877279619901.056300235
#Sta/Elev= 30
       0 3519.42     3.4 3517.74     9.7 3515.85    19.2  3509.9    32.3 3502.14
    38.2 3499.54    45.3 3496.97    49.7 3496.08    67.5 3494.46    71.5 3494.25
    75.7 3494.41      853494.315    92.7 3493.32   96.783494.044    96.83494.049
   111.5 3497.43   115.9 3498.09   126.2 3498.86   147.7 3498.88   161.6 3499.69
   175.9 3502.58   180.7 3503.36   196.8 3507.91     207  3511.7   209.3 3512.37
   214.2 3513.35     220 3515.47     229 3519.51   237.3 3522.36   243.9  3523.6
#Mann= 3 ,-1,0
       0      .1       0      85    .045       0   96.78      .1       0
Bank Sta=85,96.8
XS Rating Curve= 0 ,0
Exp/Cntr(USF)=0,0
Exp/Cntr=0.3,0.1

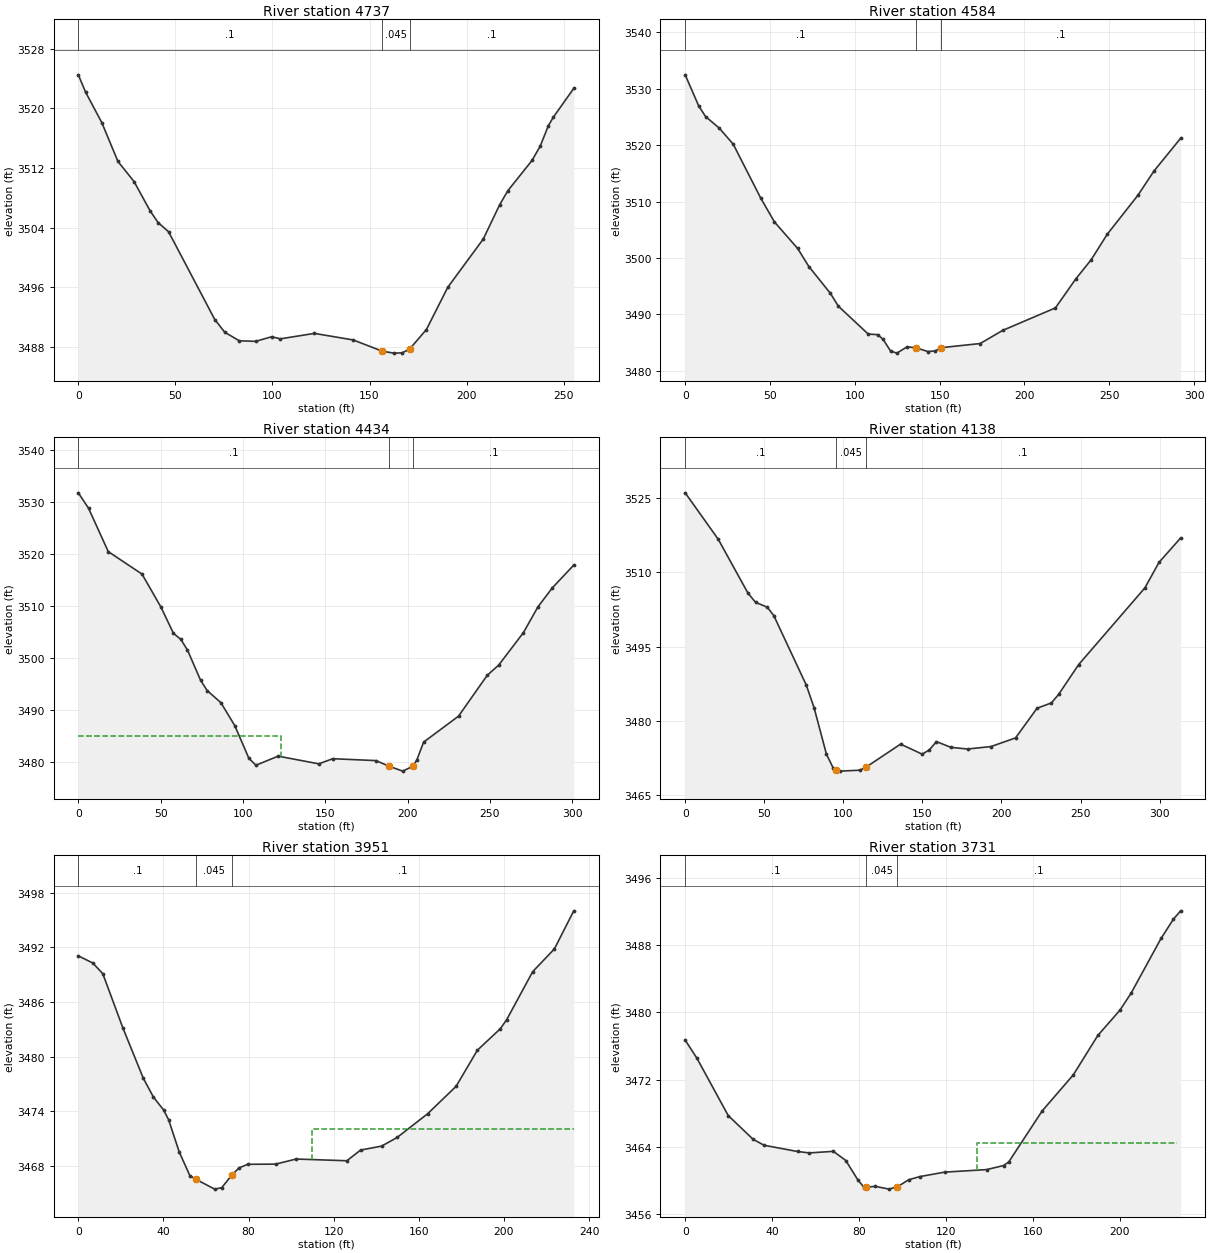
Type RM Length L Ch R = 1 ,4737    ,154.2,152.9,152.1
XS GIS Cut Line= 3
2331672.49755457620210.5922994772331725.83212078620196.031608787
2331916.66770535620136.409798258
#Sta/Elev= 30
       0 3524.51     3.8 3522.16    12.1 3518.09    20.4 3512.88    28.7 3510.18
      37 3506.23    41.1 3504.67    46.5 3503.43    70.3 3491.64    75.4 3489.94
    82.9 3488.79    91.3 3488.71    99.6 3489.33   104.1 3489.05   121.6 3489.78
   141.6  3488.9   156.53487.395   162.5 3487.13   166.7 3487.16   170.6 3487.66
   179.3  3490.3   190.3 3495.97   208.6 3502.46     217 3507.04   221.2 3508.93
   233.7 3513.01   237.9 3514.92   242.1 3517.66   244.6 3518.79   255.2 3522.69
#Mann= 3 ,-1,0
       0      .1       0   156.5    .045       0   170.6      .1       0
Bank Sta=156.5,170.6
XS Rating Curve= 0 ,0
Exp/Cntr(USF)=0,0
Exp/Cntr=0.3,0.1

Type RM Length L Ch R = 1 ,4584    ,147.8,150.1,149
XS GIS Cut Line= 3
2331680.34805143620354.0887639562331754.80214677620341.035123863
2331951.57368447620250.626579517
#Sta/Elev= 30
       0 3532.47     7.9    3527      12 3525.08    20.1 3523.02    28.3 3520.19
    44.5 3510.64    52.6 3506.41    66.3  3501.7    72.9  3498.5    85.6 3493.75
    90.3 3491.47   107.9 3486.53   113.6 3486.42   116.7 3485.57   121.1 3483.52
   124.8 3483.15   130.8 3484.26   135.83484.123   143.1 3483.43   147.5 3483.54
   150.63484.107   173.9 3484.85   187.2 3487.18   218.3 3491.17   230.3 3496.31
   239.4 3499.72   248.8 3504.21   266.9 3511.12   276.4 3515.43   292.1 3521.23
#Mann= 3 ,-1,0
       0      .1       0   135.8    .045       0   150.6      .1       0
Bank Sta=135.8,150.6
XS Rating Curve= 0 ,0
Exp/Cntr(USF)=0,0
Exp/Cntr=0.3,0.1

Type RM Length L Ch R = 1 ,4434    ,296.2,296,294.6
XS GIS Cut Line= 4
2331701.96822842620475.4715424332331782.50522854 620471.66664479
2331931.53038624620418.3980777822331987.96970128620392.397943886
#Sta/Elev= 30
       0 3531.76     6.2  3528.8    18.2 3520.46    38.7 3516.14    50.3 3509.74
    57.8 3504.75    62.3 3503.58    66.3 3501.55    74.3 3495.72    78.3 3493.74
    86.6 3491.43    95.1 3486.98   103.6 3480.74   107.9 3479.39   121.4 3481.14
   146.1 3479.66   154.6 3480.65   180.9 3480.28   188.6 3479.22   197.1 3478.26
   203.2 3479.19   205.6 3480.35   209.8 3483.84     231 3488.83   248.4 3496.67
   255.4 3498.65   270.4 3504.88   279.2 3509.82     288  3513.5     301 3517.87
#Mann= 3 ,-1,0
       0      .1       0   188.6    .045       0   203.2      .1       0
#XS Ineff= 2 , 0
          123.04 3484.93
Permanent Ineff=
       F       F
Bank Sta=188.6,203.2
XS Rating Curve= 0 ,0
Exp/Cntr(USF)=0,0
Exp/Cntr=0.3,0.1

Type RM Length L Ch R = 1 ,4138    ,191.3,187,181
XS GIS Cut Line= 4
2331789.34532763620751.1019111782331859.98971858620736.243405474
2331917.52487838620716.0984791732332076.09028833620630.573300989
#Sta/Elev= 30
       0 3526.05    20.9 3516.68    39.7 3505.81    44.5 3503.96    51.9 3502.98
      56  3501.3    76.6 3487.25    81.5  3482.7    89.3 3473.35    93.6 3470.53
   95.493470.225    95.53470.223    97.8 3469.91   110.5  3470.1   114.13470.659
   136.2 3475.36   149.8 3473.34   154.3 3474.16   158.9 3475.86     168 3474.71
   178.6 3474.37   193.4 3474.87   208.9 3476.61   222.5  3482.6   231.6 3483.67
   236.1 3485.37   248.8  3491.4   290.7 3506.88   299.6 3512.01   313.3 3516.95
#Mann= 3 ,-1,0
       0      .1       0   95.49    .045       0   114.1      .1       0
Bank Sta=95.5,114.1
XS Rating Curve= 0 ,0
Exp/Cntr(USF)=0,0
Exp/Cntr=0.3,0.1

Type RM Length L Ch R = 1 ,3951    ,220,220.3,220.3
XS GIS Cut Line= 4
2331942.48416854620916.4769071572331976.87198606620894.370453038
2332069.22838027 620771.59976035  2332099.353152  620747.9273196
#Sta/Elev= 30
       0 3491.08     6.8 3490.29    11.5 3489.12    20.9 3483.18    30.5 3477.64
    35.3 3475.55    40.1 3474.12    42.4 3473.08    47.4 3469.53    52.4 3466.92
    55.43466.492    64.1 3465.43    67.4 3465.59    72.13466.967    75.5 3467.76
    79.6 3468.16    92.7 3468.18   102.4 3468.74   126.2 3468.55   132.6 3469.72
   142.5 3470.16   149.8 3471.11   164.1 3473.71   177.5 3476.73   187.5  3480.7
   198.3 3483.07   201.2 3484.03   213.5 3489.34   223.7 3491.84   232.8 3496.03
#Mann= 3 ,-1,0
       0      .1       0    55.4    .045       0    72.1      .1       0
#XS Ineff= 2 , 0
                          109.74         3472.09
Permanent Ineff=
       F       F
Bank Sta=55.4,72.1
XS Rating Curve= 0 ,0
Exp/Cntr(USF)=0,0
Exp/Cntr=0.3,0.1

Type RM Length L Ch R = 1 ,3731    ,182.2,181.7,177.6
XS GIS Cut Line= 2
2332112.78574101 621069.584570872332254.94991241620891.396538066
#Sta/Elev= 30
       0 3476.71     5.4 3474.56    19.8 3467.75    31.2 3464.94    36.3 3464.22
    51.7 3463.48    57.1 3463.31    68.2  3463.5    73.9 3462.41    79.5 3460.09
    82.4 3459.19    83.33459.238   83.353459.241    87.5 3459.34    93.8 3459.01
    97.7  3459.3   102.9 3460.13     108  3460.5   119.4 3461.03   138.7 3461.33
   146.5 3461.81   148.9 3462.24   164.3 3468.31   178.6 3472.58   189.9 3477.27
   200.1 3480.28   205.2 3482.29     219  3488.8   224.7 3491.09     228 3492.07
#Mann= 3 ,-1,0
       0      .1       0   83.35    .045       0    97.7      .1       0
#XS Ineff= 1 ,-1
  134.18226.20983464.453
Permanent Ineff=
       F
Bank Sta=83.3,97.7
XS Rating Curve= 0 ,0
Exp/Cntr(USF)=0,0
Exp/Cntr=0.3,0.1

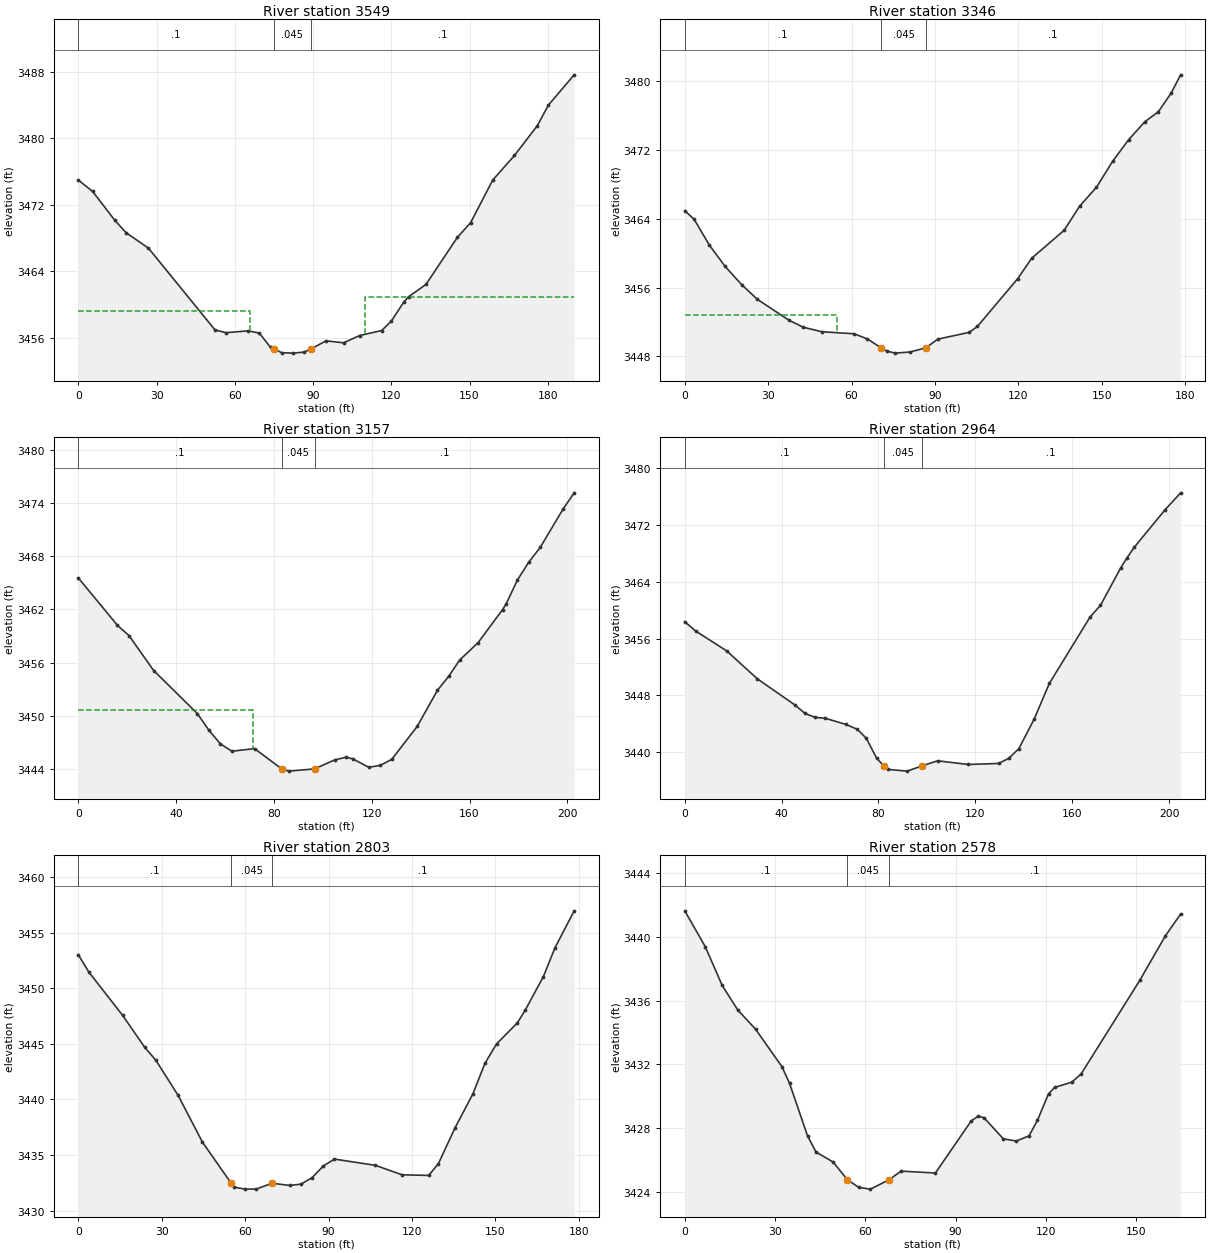
Type RM Length L Ch R = 1 ,3549    ,198,202.8,205.5
XS GIS Cut Line= 2
2332306.83128273621138.3602059072332372.33188752620959.871057835
#Sta/Elev= 30
       0 3474.98     5.5 3473.61      14 3470.14    18.3 3468.66    26.9 3466.79
    52.4 3456.96    56.6 3456.63    65.2 3456.85    69.4 3456.58    73.7 3454.86
    74.9 3454.69      78 3454.22    82.2 3454.17    86.5 3454.29    89.2 3454.67
      95 3455.65   101.7 3455.41   107.9 3456.29   116.3 3456.89     120 3458.02
   124.8 3460.32   126.6 3460.94   133.3 3462.44   145.3 3468.08   150.4 3469.86
   158.9 3474.99   167.2 3477.94     176 3481.53   180.2 3483.99   190.1 3487.64
#Mann= 3 ,-1,0
       0      .1       0    74.9    .045       0    89.2      .1       0
#XS Ineff= 2 , 0
           65.99 3459.23  110.02         3460.88
Permanent Ineff=
       F       F
Bank Sta=74.9,89.2
XS Rating Curve= 0 ,0
Exp/Cntr(USF)=0,0
Exp/Cntr=0.3,0.1

Type RM Length L Ch R = 1 ,3346    ,187.8,189.4,191.1
XS GIS Cut Line= 2
2332449.29509816621207.1358409442332578.65879263621084.322206949
#Sta/Elev= 30
       0 3464.96     3.4 3463.94     8.7 3461.02    14.5 3458.48    20.5 3456.34
    26.1 3454.65    37.4 3452.23    42.6  3451.4    49.3 3450.88    60.9 3450.64
    65.7 3450.04    70.73448.992    72.6 3448.64    75.7 3448.39    81.2 3448.53
    86.7 3449.01    91.1 3450.02   102.4 3450.81   105.3  3451.5   119.8 3457.06
   124.8 3459.42   136.5 3462.68   142.1  3465.5   148.1 3467.67   153.9 3470.68
   159.7 3473.22   165.5 3475.29   170.4 3476.47     175 3478.64   178.4 3480.76
#Mann= 3 ,-1,0
       0      .1       0    70.7    .045       0    86.7      .1       0
#XS Ineff= 2 , 0
           54.73 3452.87
Permanent Ineff=
       F       F
Bank Sta=70.7,86.7
XS Rating Curve= 0 ,0
Exp/Cntr(USF)=0,0
Exp/Cntr=0.3,0.1

Type RM Length L Ch R = 1 ,3157    ,191.6,192.9,194.5
XS GIS Cut Line= 2
 2332534.4458844621353.6934441782332708.02248711621248.892476503
#Sta/Elev= 30
       0 3465.56      16 3460.21    20.7 3459.06    30.8 3455.11    48.7 3450.24
    53.4 3448.37    58.1 3446.83    62.8    3446    72.1 3446.29    83.2    3444
    86.1 3443.75    96.63444.001   104.8 3445.01   109.4 3445.32   112.3 3445.13
   118.8 3444.18   123.5  3444.4   128.2 3445.08   138.6  3448.8   146.9 3452.88
   151.5 3454.46     156  3456.3   163.5 3458.25   173.5 3461.98   174.9 3462.58
   179.6 3465.33   184.2 3467.33   188.9    3469   198.3 3473.35   202.8 3475.17
#Mann= 3 ,-1,0
       0      .1       0    83.2    .045       0    96.6      .1       0
#XS Ineff= 2 , 0
           71.49 3450.67
Permanent Ineff=
       F       F
Bank Sta=83.2,96.6
XS Rating Curve= 0 ,0
Exp/Cntr(USF)=0,0
Exp/Cntr=0.3,0.1

Type RM Length L Ch R = 1 ,2964    ,159.8,160.9,163.1
XS GIS Cut Line= 2
2332604.85903455621507.6198654522332799.72333382621444.575533335
#Sta/Elev= 30
       0 3458.37     4.6 3457.04    17.3 3454.26      30 3450.31    45.5 3446.63
    49.7 3445.43    53.9 3444.88    58.1 3444.75    66.5 3443.89    71.3 3443.19
      75 3441.92    79.2 3439.15    82.2 3438.03      84 3437.54    91.8  3437.3
    97.83438.015   104.4 3438.76     117 3438.24   129.6 3438.38   133.8  3439.1
     138 3440.48   144.3 3444.64   150.6 3449.69   167.4 3459.04   171.7 3460.69
   180.1    3466   182.5  3467.3   185.6 3468.86   198.3 3474.14   204.8 3476.56
#Mann= 3 ,-1,0
       0      .1       0    82.2    .045       0    97.8      .1       0
Bank Sta=82.2,97.8
XS Rating Curve= 0 ,0
Exp/Cntr(USF)=0,0
Exp/Cntr=0.3,0.1

Type RM Length L Ch R = 1 ,2803    ,227.7,225,216.6
XS GIS Cut Line= 3
2332648.34238669621641.283491371 2332748.5943426621633.451307315
2332822.75882116621610.125243499
#Sta/Elev= 30
       0 3453.01     3.8 3451.45    15.9 3447.57    23.9 3444.68    27.9 3443.52
    35.9 3440.36    44.6 3436.18      553432.454      56 3432.12      60 3431.94
      64 3431.95    69.73432.466    76.1 3432.27    80.1 3432.39    84.1 3432.98
    88.1 3434.02    92.1 3434.64   106.8 3434.08   116.4 3433.23     126 3433.17
   129.5 3434.24   135.5 3437.47   141.9 3440.51   146.2 3443.24   150.4    3445
   157.9 3446.89   160.7 3448.03   167.2 3451.03   171.4 3453.63   178.3 3456.96
#Mann= 3 ,-1,0
       0      .1       0      55    .045       0    69.7      .1       0
Bank Sta=55,69.7
XS Rating Curve= 0 ,0
Exp/Cntr(USF)=0,0
Exp/Cntr=0.3,0.1

Type RM Length L Ch R = 1 ,2578    ,180.6,180.3,176.4
XS GIS Cut Line= 2
2332772.41276543621862.9908830622332882.75479709621740.600008866
#Sta/Elev= 30
       0 3441.64     6.8 3439.39    12.4 3436.97    17.6 3435.42    23.5 3434.22
    32.3 3431.86    34.8 3430.82    40.8 3427.52    43.6 3426.51    49.3 3425.88
      54 3424.78    57.8 3424.29    61.7 3424.18    67.9 3424.77    71.9 3425.31
    83.3 3425.19    95.2 3428.46    97.4 3428.74    99.4 3428.67   105.9 3427.33
   110.2  3427.2   114.4 3427.52   117.2 3428.49   120.9 3430.16   122.9 3430.56
   128.6 3430.89   131.7  3431.4   151.2 3437.27   159.7 3440.06   164.8 3441.44
#Mann= 3 ,-1,0
       0      .1       0      54    .045       0    67.9      .1       0
Bank Sta=54,67.9
XS Rating Curve= 0 ,0
Exp/Cntr(USF)=0,0
Exp/Cntr=0.3,0.1

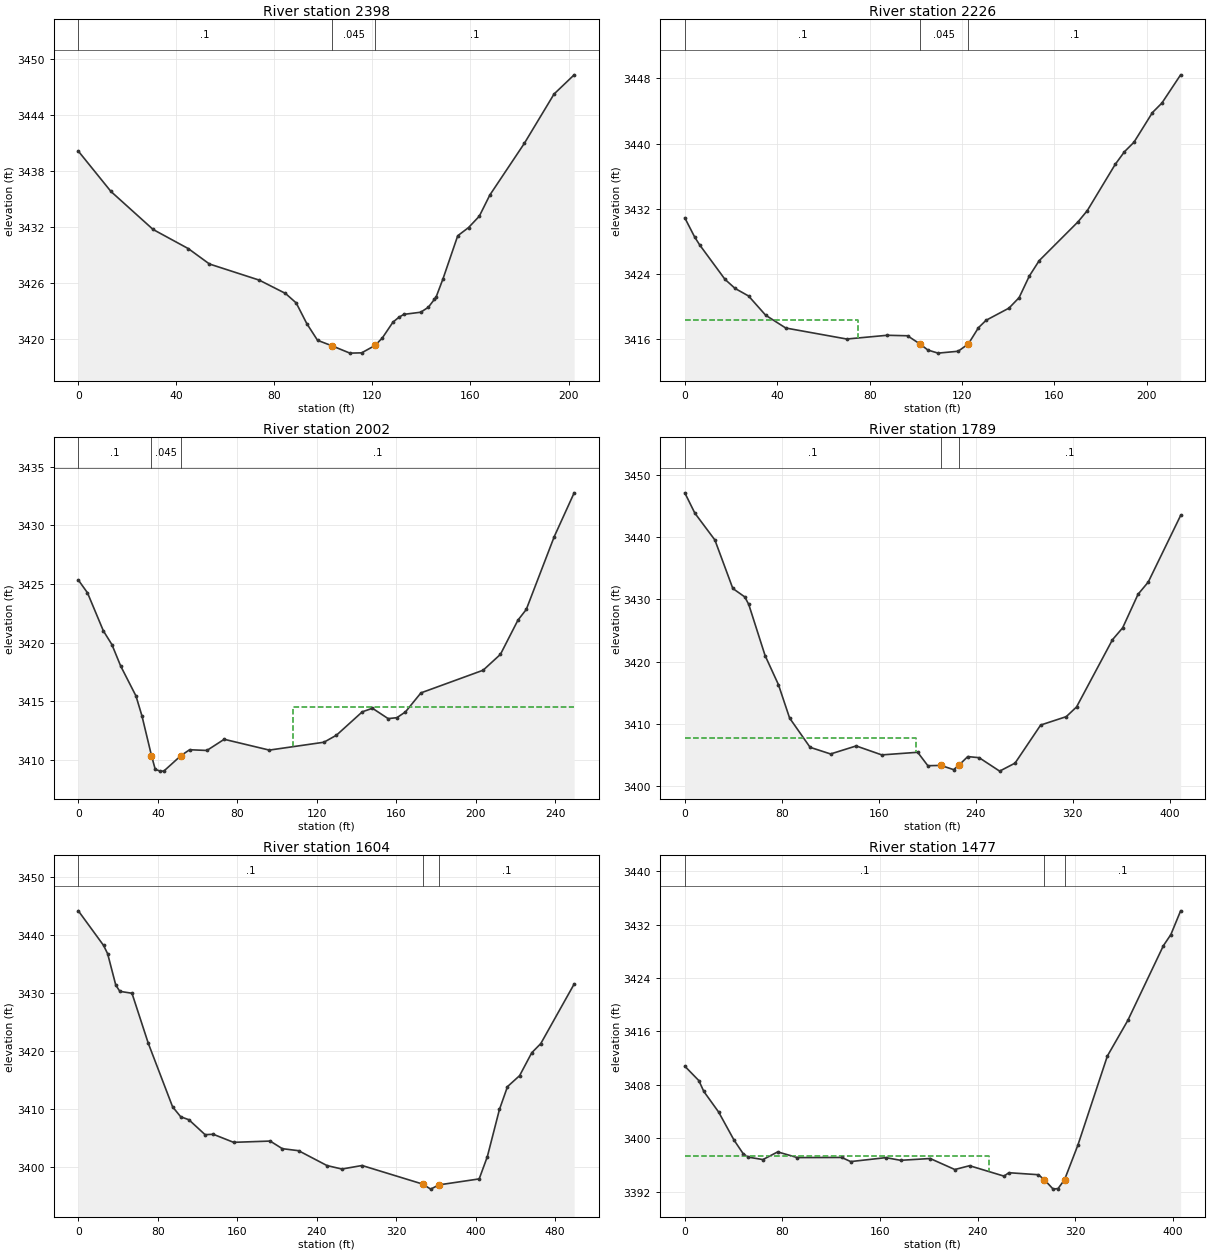
Type RM Length L Ch R = 1 ,2398    ,171.4,171.8,171.5
XS GIS Cut Line= 3
2332895.93318781621963.5140762922332960.99248228621917.554758179
2333011.72679449621805.939271331
#Sta/Elev= 30
       0 3440.12    13.3 3435.81    30.5 3431.75    44.9  3429.7    53.5 3428.06
    73.8 3426.34    84.5 3424.92    88.9  3423.9    93.2  3421.7    97.6 3419.91
   103.5 3419.32   110.8 3418.54   115.6 3418.57   121.13419.367     124 3420.15
   128.4 3421.86   130.7 3422.35   132.8 3422.68   139.7 3422.91   142.8 3423.44
   145.3 3424.29     146 3424.55   148.8 3426.49   154.8 3431.08   159.2 3431.95
   163.6 3433.17   167.9 3435.43     182 3440.96   194.1 3446.22   202.3 3448.27
#Mann= 3 ,-1,0
       0      .1       0   103.5    .045       0   121.1      .1       0
Bank Sta=103.5,121.1
XS Rating Curve= 0 ,0
Exp/Cntr(USF)=0,0
Exp/Cntr=0.3,0.1

Type RM Length L Ch R = 1 ,2226    ,220.1,224.2,221.7
XS GIS Cut Line= 3
2333087.52982566622053.0452154752333153.78286865621906.214147215
2333160.34848553621853.092337967
#Sta/Elev= 30
       0  3430.9     4.2 3428.58     6.4 3427.59    17.4 3423.35    21.8 3422.23
    27.6 3421.31      35 3418.95    43.7 3417.38    70.1 3416.03    87.6 3416.49
    96.4 3416.43   101.9  3415.4   105.2 3414.68   109.6  3414.3   118.3 3414.53
   122.7 3415.42   127.1 3417.42   130.4 3418.33   140.3 3419.82   144.7 3421.11
   149.1 3423.75   153.4 3425.65   170.2 3430.41   174.2 3431.78   186.3 3437.46
   190.3 3439.01   194.4 3440.17   202.4 3443.81   206.5 3444.98   214.6 3448.44
#Mann= 3 ,-1,0
       0      .1       0   101.9    .045       0   122.7      .1       0
#XS Ineff= 2 , 0
           75.09  3418.4
Permanent Ineff=
       F       F
Bank Sta=101.9,122.7
XS Rating Curve= 0 ,0
Exp/Cntr(USF)=0,0
Exp/Cntr=0.3,0.1

Type RM Length L Ch R = 1 ,2002    ,211.7,212.9,209.8
XS GIS Cut Line= 2
2333261.81710993622140.7857318732333359.10761451621910.989141305
#Sta/Elev= 30
       0 3425.34     4.6 3424.25    12.6 3421.01    16.9 3419.84    21.3 3418.02
      29 3415.47      32 3413.78    36.8  3410.4    38.7 3409.22    41.2 3409.07
      43 3409.07    51.7  3410.4      56 3410.89    64.7 3410.83    73.4 3411.78
    96.1 3410.86   123.6 3411.53   129.9 3412.13   142.9 3414.12     148 3414.42
   155.9 3413.54   160.3 3413.62   164.6 3414.11   172.4 3415.73   203.7 3417.66
   212.4 3419.01   221.2 3421.92   225.4 3422.83   239.5 3429.04   249.5 3432.76
#Mann= 3 ,-1,0
       0      .1       0    36.8    .045       0    51.7      .1       0
#XS Ineff= 2 , 0
                          107.92         3414.52
Permanent Ineff=
       F       F
Bank Sta=36.8,51.7
XS Rating Curve= 0 ,0
Exp/Cntr(USF)=0,0
Exp/Cntr=0.3,0.1

Type RM Length L Ch R = 1 ,1789    ,185.6,185.1,183.1
XS GIS Cut Line= 3
2333360.19084811622285.5863394122333434.80013076622265.889488792
2333541.64062352621951.933627392
#Sta/Elev= 30
       0 3447.15     8.3 3443.88    24.8 3439.57    39.6 3431.77    49.4 3430.42
    52.7 3429.22    66.2 3420.98    77.2 3416.31    86.4 3410.94   103.3 3406.23
   120.2 3405.16   141.3 3406.45   162.4 3405.01     192 3405.43   200.4 3403.27
   211.2 3403.32   221.6 3402.64   225.8 3403.32   233.3 3404.74   242.7 3404.56
   259.6  3402.4   272.3 3403.69   293.4 3409.81   314.5 3411.16     323 3412.72
   352.6 3423.53     361 3425.44   373.7 3430.84   382.1  3432.8   408.8 3443.51
#Mann= 3 ,-1,0
       0      .1       0   211.2    .045       0   225.8      .1       0
#XS Ineff= 2 , 0
          190.25 3407.77
Permanent Ineff=
       F       F
Bank Sta=211.2,225.8
XS Rating Curve= 0 ,0
Exp/Cntr(USF)=0,0
Exp/Cntr=0.3,0.1

Type RM Length L Ch R = 1 ,1604    ,125.9,126.8,125
XS GIS Cut Line= 3
 2333379.3211185622323.4325888642333629.86093185622270.213347466
2333673.25508253622031.136139956
#Sta/Elev= 30
       0 3444.21    25.4 3438.25    29.5 3436.82    37.7 3431.41    41.8 3430.34
      54 3430.01    70.4  3421.4    94.9 3410.44   103.1 3408.73   111.3 3408.22
   127.6 3405.65   135.8 3405.72   156.3 3404.33   193.1 3404.55   205.3 3403.24
   221.7 3402.89   250.3 3400.33   265.3 3399.73   285.6 3400.34   346.6 3397.14
   354.7 3396.27   362.9    3397   403.5 3398.03   411.7 3401.86   423.9    3410
     432 3413.93   444.2 3415.82   456.4 3419.76   465.5 3421.34   499.1  3431.6
#Mann= 3 ,-1,0
       0      .1       0   346.6    .045       0   362.9      .1       0
Bank Sta=346.6,362.9
XS Rating Curve= 0 ,0
Exp/Cntr(USF)=0,0
Exp/Cntr=0.3,0.1

Type RM Length L Ch R = 1 ,1477    ,314.4,320.3,317.6
XS GIS Cut Line= 3
2333730.56811172622480.6340403782333774.78101996622129.387047152
 2333794.4312014622081.080351114
#Sta/Elev= 30
       0  3410.8    11.5 3408.64    15.6 3407.01    27.7 3403.93    40.3 3399.73
    47.8 3397.69    51.9 3397.17      64  3396.8    76.1 3397.95    92.2  3397.1
   128.5 3397.12   135.9  3396.5   164.7 3397.09   176.8 3396.69     201 3396.96
   221.2 3395.31   233.3 3395.88   261.5 3394.32   265.5 3394.83   289.7 3394.53
   294.6 3393.77   301.8 3392.37   305.8 3392.46   311.1 3393.78     322 3398.95
   346.2 3412.33   362.9 3417.65   392.1 3428.87   398.2 3430.53   406.2 3434.09
#Mann= 3 ,-1,0
       0      .1       0   294.6    .045       0   311.1      .1       0
#XS Ineff= 2 , 0
          249.46 3397.32
Permanent Ineff=
       F       F
Bank Sta=294.6,311.1
XS Rating Curve= 0 ,0
Exp/Cntr(USF)=0,0
Exp/Cntr=0.3,0.1

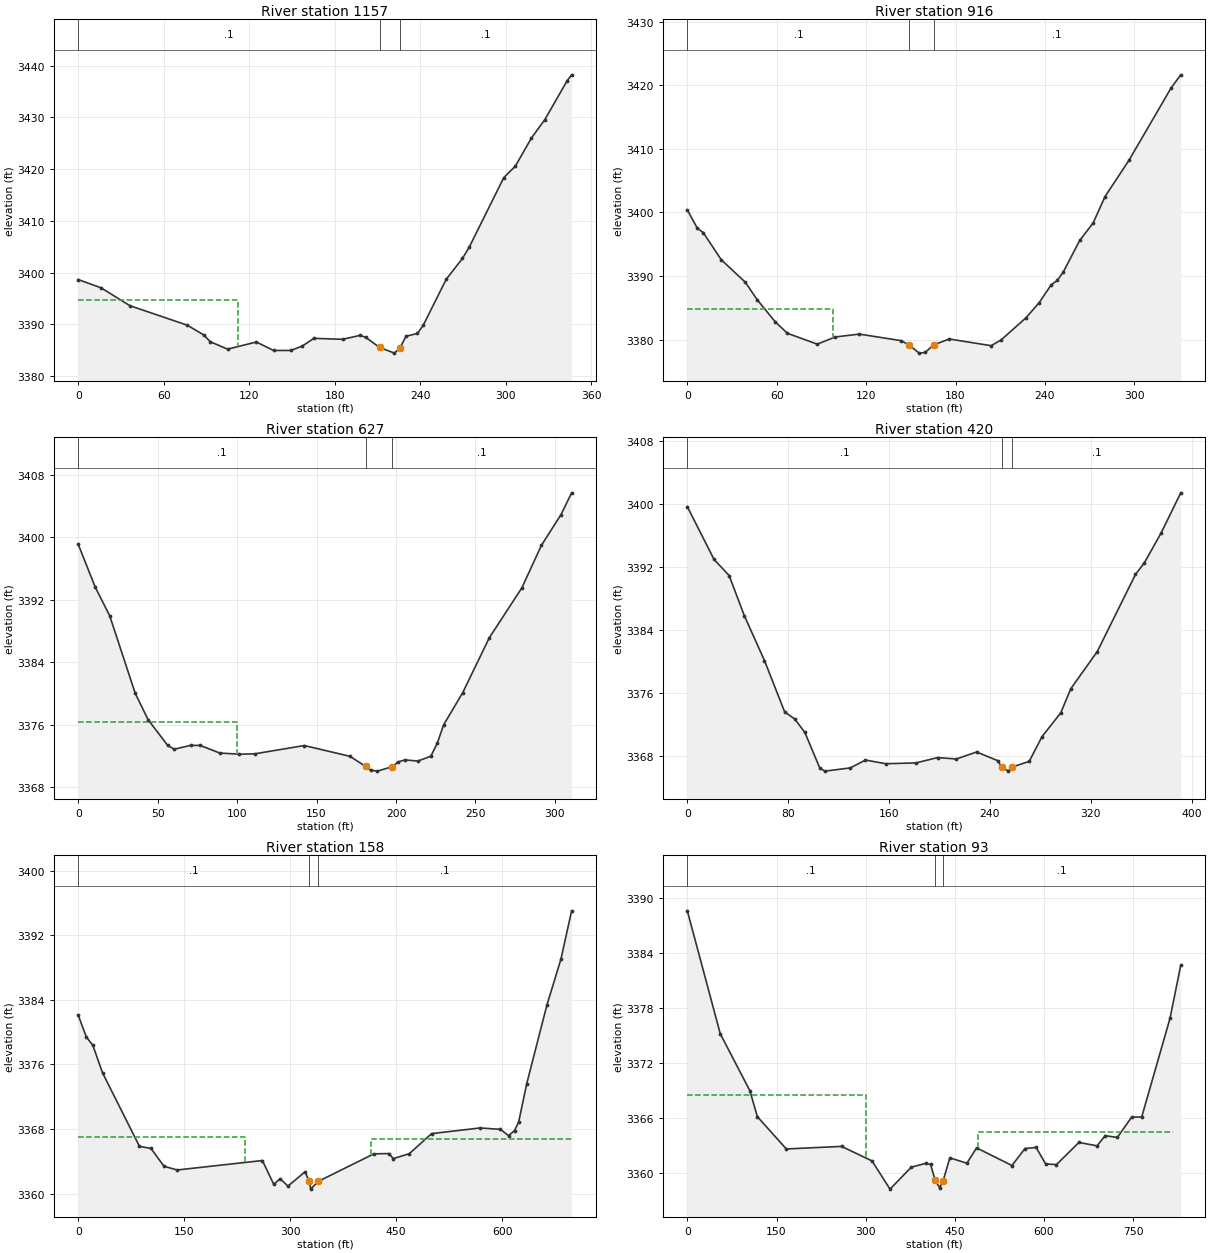
Type RM Length L Ch R = 1 ,1157    ,240.6,240.3,236.5
XS GIS Cut Line= 2
2334000.58386974622497.0327494542334047.25305065622153.973331828
#Sta/Elev= 30
       0 3398.65      16 3397.06    36.2 3393.61    76.6 3389.82    88.3  3387.9
    92.7 3386.63   104.8  3385.2     125 3386.58   137.1 3384.94   149.2 3384.95
   157.3 3385.81   165.4 3387.29   185.5  3387.1   197.7 3387.86   201.7 3387.49
   211.53385.521   221.9 3384.43   225.9 3385.49     230 3387.69     238 3388.23
   242.1 3389.82   258.2  3398.7   269.6 3402.73   274.4 3404.94   298.6 3418.36
   306.7 3420.57     318 3426.01   327.4 3429.57     343 3437.06   346.2 3438.23
#Mann= 3 ,-1,0
       0      .1       0   211.5    .045       0   225.9      .1       0
#XS Ineff= 2 , 0
           112.2 3394.72
Permanent Ineff=
       F       F
Bank Sta=211.5,225.9
XS Rating Curve= 0 ,0
Exp/Cntr(USF)=0,0
Exp/Cntr=0.3,0.1

Type RM Length L Ch R = 1 ,916     ,290.9,289.3,285.8
XS GIS Cut Line= 2
2334261.76753137622515.8641733332334225.74219873622186.723634226
#Sta/Elev= 30
       0  3400.4     6.7 3397.53    10.7 3396.83    22.8 3392.56    38.9 3389.04
      47 3386.25      59 3382.82    67.1 3381.02    87.2 3379.31    99.3 3380.44
   115.4 3380.89   143.5 3379.86     149 3379.15   155.6  3377.9   159.6 3378.01
   165.33379.186   175.7 3380.12   203.9 3379.07   210.6 3379.98   227.2 3383.44
   236.1 3385.83   244.1 3388.61   248.2 3389.32   252.2 3390.61   263.3 3395.61
   272.3 3398.34   280.3  3402.5   296.4 3408.22   324.6 3419.56   331.1 3421.63
#Mann= 3 ,-1,0
       0      .1       0     149    .045       0   165.3      .1       0
#XS Ineff= 2 , 0
           97.54 3384.88
Permanent Ineff=
       F       F
Bank Sta=149,165.3
XS Rating Curve= 0 ,0
Exp/Cntr(USF)=0,0
Exp/Cntr=0.3,0.1

Type RM Length L Ch R = 1 ,627     ,205.8,206.9,207.7
XS GIS Cut Line= 5
2334542.60137444622448.7260534162334536.05131396622404.513145178
2334508.21355692622278.4244809432334497.56970864622254.680511704
 2334473.8257394622146.604513788
#Sta/Elev= 30
       0 3399.11    10.8 3393.58    19.8 3389.96    35.9 3379.99      44 3376.62
    56.3 3373.33    60.4 3372.84    70.9 3373.34    76.8 3373.32    89.1 3372.35
   101.4  3372.2   111.1 3372.25   142.3 3373.31     171 3371.93   180.8 3370.64
     184 3370.15   188.3 3370.03   197.73370.611   201.4 3371.22   205.6 3371.47
   213.7 3371.32   221.9 3371.94     226 3373.63     230 3375.98     242  3380.1
   258.7 3387.13   279.2 3393.53   291.5 3398.98   303.8 3402.91   310.5 3405.71
#Mann= 3 ,-1,0
       0      .1       0   180.8    .045       0   197.7      .1       0
#XS Ineff= 2 , 0
          100.09 3376.29
Permanent Ineff=
       F       F
Bank Sta=180.8,197.7
XS Rating Curve= 0 ,0
Exp/Cntr(USF)=0,0
Exp/Cntr=0.3,0.1

Type RM Length L Ch R = 1 ,420     ,262.1,262.6,260
XS GIS Cut Line= 4
2334709.62791667622450.3635685362334702.12274616622225.520881329
2334677.69637183622141.6919684292334631.02719091622077.828878751
#Sta/Elev= 30
       0 3399.69    21.2 3392.99    33.2 3390.94    45.2 3385.85    61.2 3380.15
    77.2 3373.63    85.2 3372.73    93.2 3371.03   105.2 3366.46   109.2 3366.11
   129.3 3366.52   141.3 3367.52   157.3 3367.05   181.3 3367.15   198.5 3367.83
   213.3 3367.65   229.5 3368.54   246.2 3367.44   249.4 3366.64   254.5 3366.12
   257.9 3366.64   271.2 3367.35   281.4  3370.5   296.2 3373.51   304.2 3376.58
   325.2  3381.3   355.5 3391.09   362.5 3392.55   375.9 3396.37   391.4 3401.45
#Mann= 3 ,-1,0
       0      .1       0   249.4    .045       0   257.9      .1       0
Bank Sta=249.4,257.9
XS Rating Curve= 0 ,0
Exp/Cntr(USF)=0,0
Exp/Cntr=0.3,0.1

Type RM Length L Ch R = 1 ,158     ,65,64.6,64.1
XS GIS Cut Line= 4
2334794.09808962622565.040167521 2334923.4617841622492.989502244
2334891.81441509622226.333260875 2334663.8195261622060.657978611
#Sta/Elev= 30
       0  3382.1    11.5 3379.39    20.7 3378.37    34.4 3374.97    86.7 3365.86
   103.1  3365.6   121.4  3363.4   140.1 3362.94   260.7 3364.11   276.8 3361.16
   285.8 3361.86   296.9 3360.94   321.1 3362.72   326.9 3361.54   329.1 3360.57
339.49963361.518   418.6 3364.94   440.1 3364.97   445.8 3364.34   468.7 3364.96
   500.2 3367.44   568.9 3368.14   597.6 3367.97   609.1 3367.19   617.6 3367.81
   623.4 3368.86   634.8  3373.6   663.5 3383.37   683.2 3389.01   698.4 3395.01
#Mann= 3 ,-1,0
       0      .1       0   326.9    .045       0339.4996      .1       0
#XS Ineff= 2 , 0
          235.88 3367.04  414.15         3366.78
Permanent Ineff=
       F       F
Bank Sta=326.9,339.4996
XS Rating Curve= 0 ,0
Exp/Cntr(USF)=0,0
Exp/Cntr=0.3,0.1

Type RM Length L Ch R = 1 ,93      ,58.3,56.3,51.4
XS GIS Cut Line= 4
2334783.64925509622605.4721448292334994.14108903622449.751145237
2334935.51151286622146.6700884872334725.30503714621994.650214082
#Sta/Elev= 30
       0 3388.55    55.4 3375.17   105.1 3368.99   117.8 3366.15   166.5 3362.64
   259.4 3362.92   310.6 3361.34   340.9 3358.27   376.7 3360.66   400.9 3361.07
   409.1 3360.95   416.7 3359.27   424.4 3358.42430.29963359.188   441.5 3361.67
   470.2 3361.09   486.5 3362.76     546 3360.84     568 3362.69   586.7  3362.8
   602.6 3361.01   620.9 3360.94   658.6 3363.35   689.1 3362.98   702.8 3364.09
   723.2 3363.89   747.4 3366.11   764.2 3366.11   811.8 3376.84   829.9 3382.63
#Mann= 3 ,-1,0
       0      .1       0   416.7    .045       0430.2996      .1       0
#XS Ineff= 2 ,-1
       0  300.983368.463  488.09817.3177 3364.47
Permanent Ineff=
       F       F
Bank Sta=416.7,430.2996
XS Rating Curve= 0 ,0
Exp/Cntr(USF)=0,0
Exp/Cntr=0.3,0.1