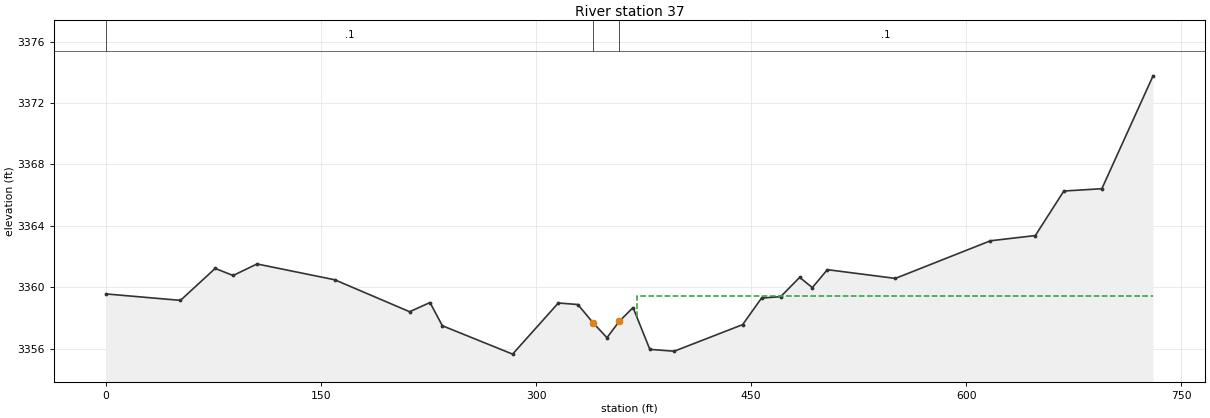
HEC-RAS study CAMPFIVERN.prj: CAMPFIVERN

--- CAMPFIVERN.g01 (geometry) --- (continued)

Type RM Length L Ch R = 1 ,37      ,,,
XS GIS Cut Line= 6
2334988.76175215 622594.321560862335062.76106865622341.175534474
 2335002.9723068622259.5111057352334979.90577881622216.483319121
2334942.59083831622137.5496437482334764.38180343621993.505035243
#Sta/Elev= 30
       0 3359.57      52 3359.15    76.2 3361.23    88.7 3360.77   105.4 3361.52
   159.6 3360.49   211.8 3358.41     226 3359.01   234.6  3357.5   283.6 3355.65
   315.5 3358.98   329.1 3358.88     340 3357.66   349.4 3356.72   357.9 3357.78
   367.6 3358.68   379.3 3355.96   396.3 3355.84     444 3357.57   457.2  3359.3
   470.5 3359.39   483.8 3360.65   492.6 3359.98   503.1 3361.15   550.5 3360.58
   616.8 3363.03   648.1 3363.37     668 3366.27   694.5 3366.42   730.2 3373.77
#Mann= 3 ,0,0
       0      .1       0     340    .045       0   357.9      .1       0
#XS Ineff= 2 , 0
                          370.13         3359.43
Permanent Ineff=
       F       F
Bank Sta=340,357.9
XS Rating Curve= 0 ,0
Exp/Cntr(USF)=0,0
Exp/Cntr=0.3,0.1
LCMann Table=0

Chan Stop Cuts=-1
Use User Specified Reach Order=0
Composite Channel Slope=5